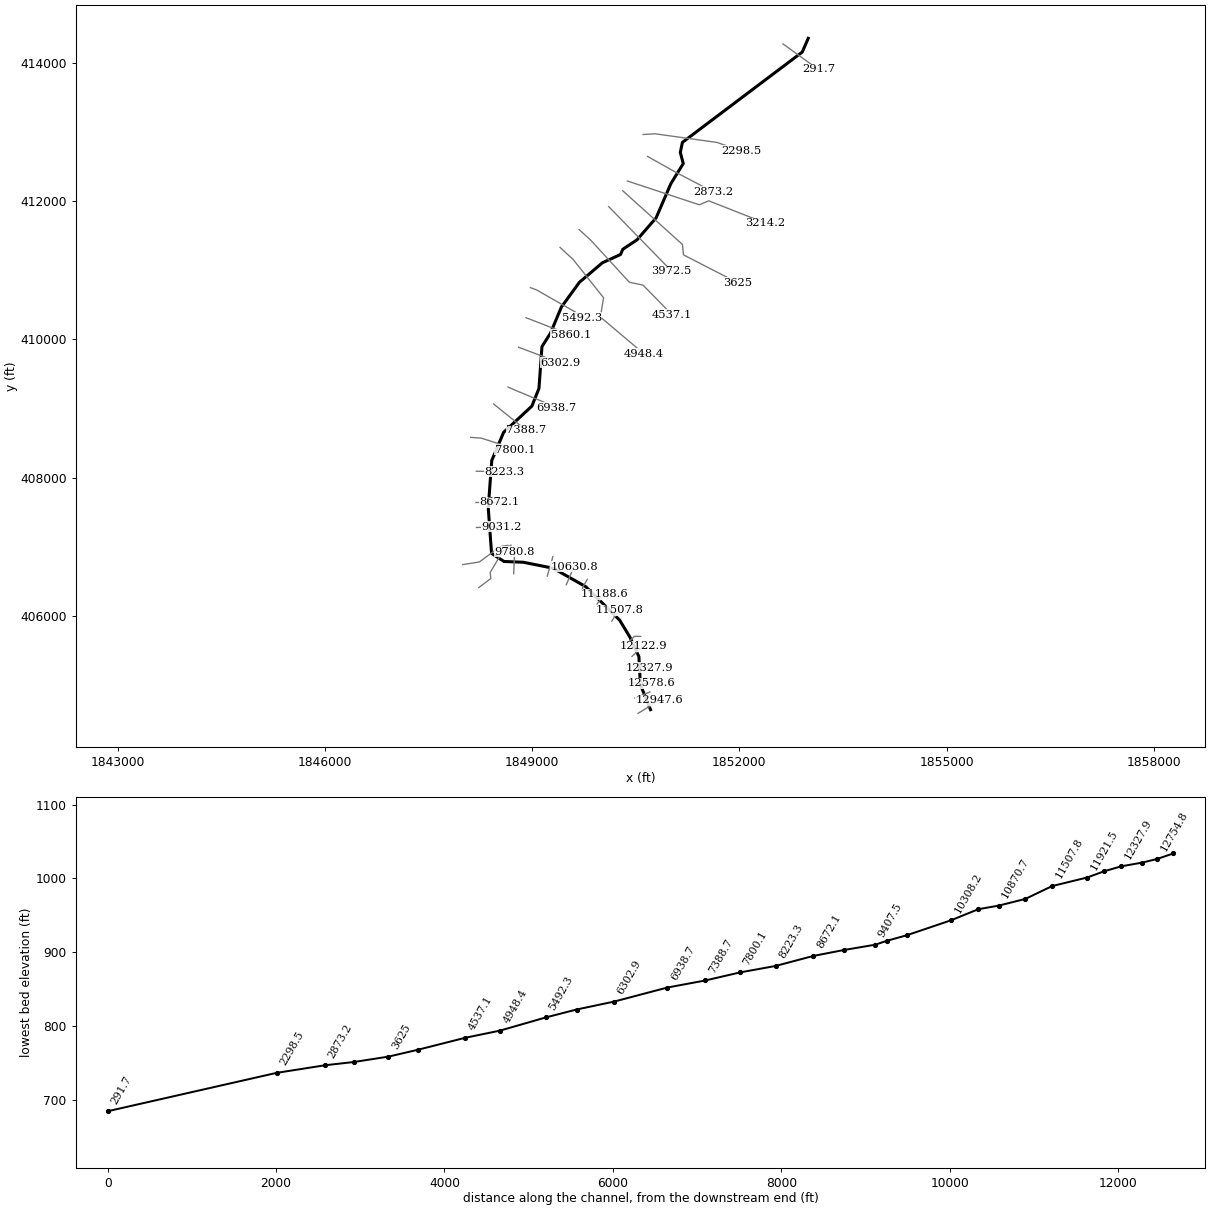
--- FOURMLEFK2.prj (project) ---

Proj Title=FOURMLEFK2
Current Plan=p01
Default Exp/Contr=0,0
English Units
Geom File=g01
Flow File=f01
Plan File=p01
BEGIN DESCRIPTION:
END DESCRIPTION:
DSS Export Rating Curves= 0
DSS Export Rating Curve Sorted= 0
DSS Export Volume Flow Curves= 0
DXF OffsetX= 0
DXF OffsetY= 0
DXF ScaleX= 0
DXF ScaleY= 0

--- FOURMLEFK2.p01 (plan) ---

Plan Title=Floodplain
Program Version=4.00
Geom File=g01
Flow File=f01
K Sum by GR=0
Std Step Tol=0.01
Critical Tol=0.01
Num of Std Step Trials=20
Max Error Tol=0.3
Flow Tol Ratio=0.001
Split Flow NTrial=30
Split Flow Tol=0.02
Split Flow Ratio=0.02
Log Output Level=0
Friction Slope Method=1
Unsteady Friction Slope Method=2
Unsteady Bridges Friction Slope Method=1
Global Log Level=0
CheckData=False
Run HTab=0
Run UNet=0
Run PostProcess=0
UNET Theta=0
UNET Theta Warmup=0
UNET ZTol=0
UNET ZSATol=0
UNET MxIter=0
UNET MaxInSteps=0
UNET DtIC=0
UNET DtMin=0
UNET MaxCRTS=0
UNET WFStab=0
UNET SFStab=0
UNET WFX=0
UNET SFX=0
UNET DSS MLevel=0
UNET DZMax Abort=0
UNET Convert EG Bridges=0
UNET Use Existing IB Tables=0
UNET Froude Limit=0
UNET Froude Power=0
Write IC File=0
Echo Input=False
Echo Output=False
Write Detailed=0

--- FOURMLEFK2.f01 (steady flow) ---

Flow Title=NFF Regression Equation
Program Version=4.10
Number of Profiles= 1
Profile Names=P100yr
River Rch & RM=FOURMLEFK2,Main            ,12947.6
919.3884
River Rch & RM=FOURMLEFK2,Main            ,10870.7
1005.313
River Rch & RM=FOURMLEFK2,Main            ,9031.2
1111.011
River Rch & RM=FOURMLEFK2,Main            ,6302.9
1191.903
River Rch & RM=FOURMLEFK2,Main            ,4537.1
1347.375
River Rch & RM=FOURMLEFK2,Main            ,2873.2
1440.875
Boundary for River Rch & Prof#=FOURMLEFK2,Main            , 1
Up Type= 0
Dn Type= 3
Dn Slope=0.02
DSS Import GetInterval= 0
DSS Import GetPeak= 0
DSS Import FillOption= 0

--- FOURMLEFK2.g01 (geometry) ---

Geom Title=USGS 10m DEM
Program Version=4.10

River Reach=FOURMLEFK2      ,Main
Reach XY= 30
     1850713.832      404649.508     1850566.696      405011.487
     1850545.596      405416.907      1850413.05      405701.591
      1850266.64      405943.593     1849776.332      406426.851
     1849303.675      406693.778     1848872.686      406779.716
     1848592.449      406791.087     1848412.761      406908.275
     1848364.873      407567.476     1848415.655      408249.768
      1848587.53       408657.32     1848996.384      409036.226
     1849098.771      409291.067     1849142.429      409896.025
     1849265.783      410090.936     1849423.467      410467.216
     1849683.884      410825.289     1850017.217      411107.841
     1850280.238      411227.633     1850311.488      411301.851
     1850517.217       411438.57     1850794.444      411756.991
     1851009.405      412253.674      1851187.79      412541.435
     1851144.821      412702.893      1851175.49      412848.044
     1852909.877      414152.882     1852996.384       414351.33

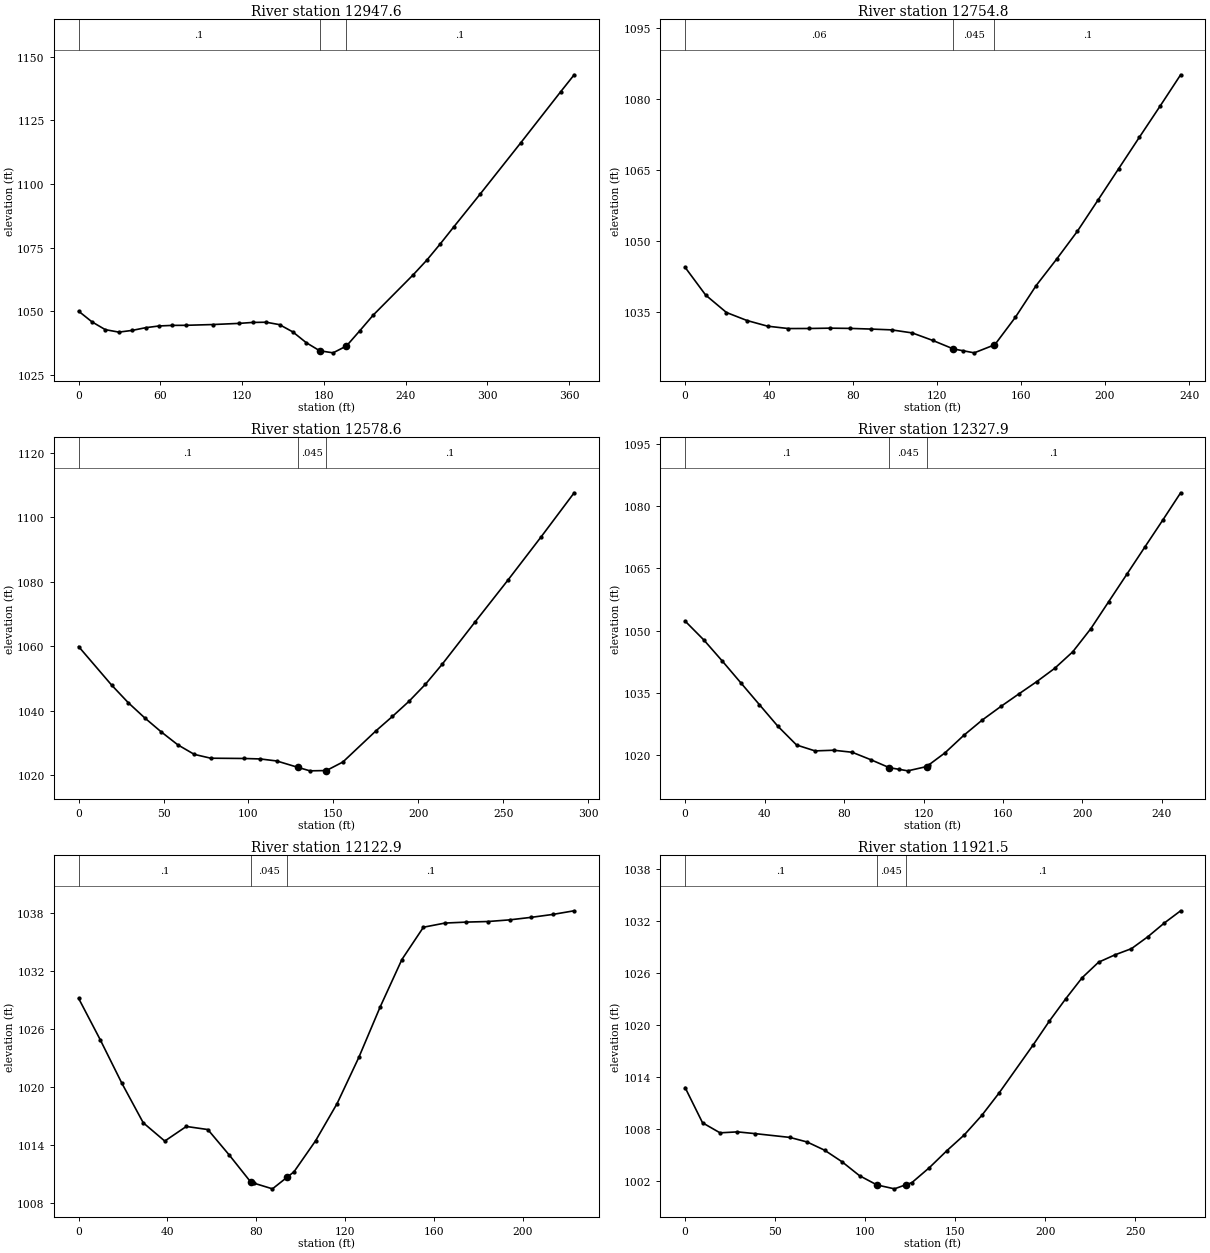
Type RM Length L Ch R = 1 ,12947.6 ,196.4,192.7,188.9
XS GIS Cut Line= 2
     1850533.103      404595.688     1850842.998      404785.792
#Sta/Elev= 30
       0 1050.08     9.8 1045.89    19.6 1042.83    29.5 1041.87    39.3 1042.54
    49.1  1043.6      59 1044.28    68.8 1044.51    78.6 1044.54    98.3 1044.84
   117.9  1045.3   127.7 1045.67   137.6 1045.75   147.4  1044.8   157.2 1041.94
     167 1037.73   176.9 1034.55   186.7 1033.74     196 1036.28   196.5 1036.42
   206.3  1042.4   216.2 1048.58   245.6 1064.42   255.5 1070.13   265.3 1076.45
   275.1 1083.05   294.8 1096.15   324.3 1116.07   353.7 1136.18   363.6 1142.83
#Mann= 3 , 0 , 0
       0      .1       0   176.9    .045       0     196      .1       0
Bank Sta=176.9,196
XS Rating Curve= 0 ,0
Exp/Cntr=0.3,0.1

Type RM Length L Ch R = 1 ,12754.8 ,185.5,176.3,167
XS GIS Cut Line= 2
     1850486.228      404817.042     1850704.978      404905.584
#Sta/Elev= 27
       0 1044.37     9.8 1038.48    19.7 1034.79    29.5 1033.09    39.3 1031.89
    49.2 1031.39      59  1031.4    68.8 1031.47    78.7 1031.42    88.5 1031.28
    98.3 1031.11   108.2 1030.46     118 1028.86   127.8 1027.06   132.2  1026.7
   137.7 1026.24   147.2 1027.91   147.5 1027.96   157.3 1033.78   167.2 1040.51
     177 1046.14   186.8    1052   196.7 1058.66   206.5 1065.29   216.3 1071.91
   226.2 1078.53     236 1085.18
#Mann= 3 , 0 , 0
       0     .06       0   127.8    .045       0   147.2      .1       0
Bank Sta=127.8,147.2
XS Rating Curve= 0 ,0
Exp/Cntr=0.3,0.1

Type RM Length L Ch R = 1 ,12578.6 ,249.7,250.7,251
XS GIS Cut Line= 2
     1850428.936      405041.001     1850720.603      405033.188
#Sta/Elev= 24
       0 1059.91    19.4 1047.97    29.2  1042.5    38.9 1037.78    48.6 1033.44
    58.4 1029.41    68.1 1026.44    77.8 1025.25    97.3 1025.17     107 1025.02
   116.7 1024.39     129 1022.43   136.2 1021.33   145.9 1021.42   155.6 1024.07
   175.1 1033.76   184.8 1038.23   194.5  1042.9   204.2  1048.2     214 1054.37
   233.4 1067.53   252.9 1080.62   272.3 1093.95   291.8 1107.66
#Mann= 3 , 0 , 0
       0      .1       0     129    .045       0   145.9      .1       0
Bank Sta=129,145.9
XS Rating Curve= 0 ,0
Exp/Cntr=0.3,0.1

Type RM Length L Ch R = 1 ,12327.9 ,188.6,205,221.5
XS GIS Cut Line= 3
     1850447.165      405283.188     1850606.019      405283.188
     1850691.957      405254.542
#Sta/Elev= 30
       0  1052.3     9.4 1047.77    18.7 1042.69      28 1037.46    37.4 1032.18
    46.7 1026.98    56.1 1022.47    65.4 1021.05    74.8 1021.21    84.1 1020.72
    93.4 1018.94   102.8 1017.01   107.6 1016.62   112.1 1016.25   121.5 1017.27
   122.6 1017.66   130.8 1020.58   140.2 1024.77   149.5 1028.46   158.9 1031.74
   167.9 1034.74     177 1037.73     186 1040.92   195.1  1044.9   204.2 1050.47
   213.2 1056.98   222.3 1063.55   231.3 1070.06   240.4  1076.6   249.4 1083.18
#Mann= 3 , 0 , 0
       0      .1       0   102.8    .045       0   121.5      .1       0
Bank Sta=102.8,121.5
XS Rating Curve= 0 ,0
Exp/Cntr=0.3,0.1

Type RM Length L Ch R = 1 ,12122.9 ,199.5,201.3,202.7
XS GIS Cut Line= 2
     1850444.561      405418.605     1850611.228      405567.042
#Sta/Elev= 26
       0 1029.13     9.7 1024.87    19.4 1020.39    29.1 1016.27    38.8 1014.38
    48.5 1015.89    58.2 1015.57    67.9 1012.92    77.6 1010.12    78.9 1010.03
    87.3 1009.44    93.9 1010.64      97  1011.2   106.7  1014.4   116.4 1018.25
   126.2 1023.03   135.8 1028.24   145.6 1033.15   155.3 1036.49     165 1036.92
   174.7 1037.02   184.4 1037.08   194.1 1037.25   203.8 1037.51   213.5 1037.81
   223.2 1038.19
#Mann= 3 , 0 , 0
       0      .1       0    77.6    .045       0    93.9      .1       0
Bank Sta=77.6,93.9
XS Rating Curve= 0 ,0
Exp/Cntr=0.3,0.1

Type RM Length L Ch R = 1 ,11921.5 ,410.8,413.7,416.9
XS GIS Cut Line= 3
     1850350.811      405580.063     1850481.019      405710.271
     1850572.165      405707.667
#Sta/Elev= 29
       0 1012.77     9.7 1008.69    19.4 1007.53    29.1 1007.64    38.8 1007.44
    58.2    1007    67.8 1006.47    77.5 1005.52    87.2 1004.18    96.9 1002.57
   106.6  1001.5   116.3 1001.05   122.6 1001.52     126 1001.77   135.7  1003.5
   145.4 1005.46   155.1 1007.29   164.8 1009.54   174.4 1012.13   193.3 1017.68
   202.4 1020.47   211.5 1023.05   220.6 1025.48   229.7 1027.27   238.8 1028.12
     248 1028.84   257.1 1030.22   266.2  1031.8   275.3 1033.22
#Mann= 3 , 0 , 0
       0      .1       0   106.6    .045       0   122.6      .1       0
Bank Sta=106.6,122.6
XS Rating Curve= 0 ,0
Exp/Cntr=0.3,0.1

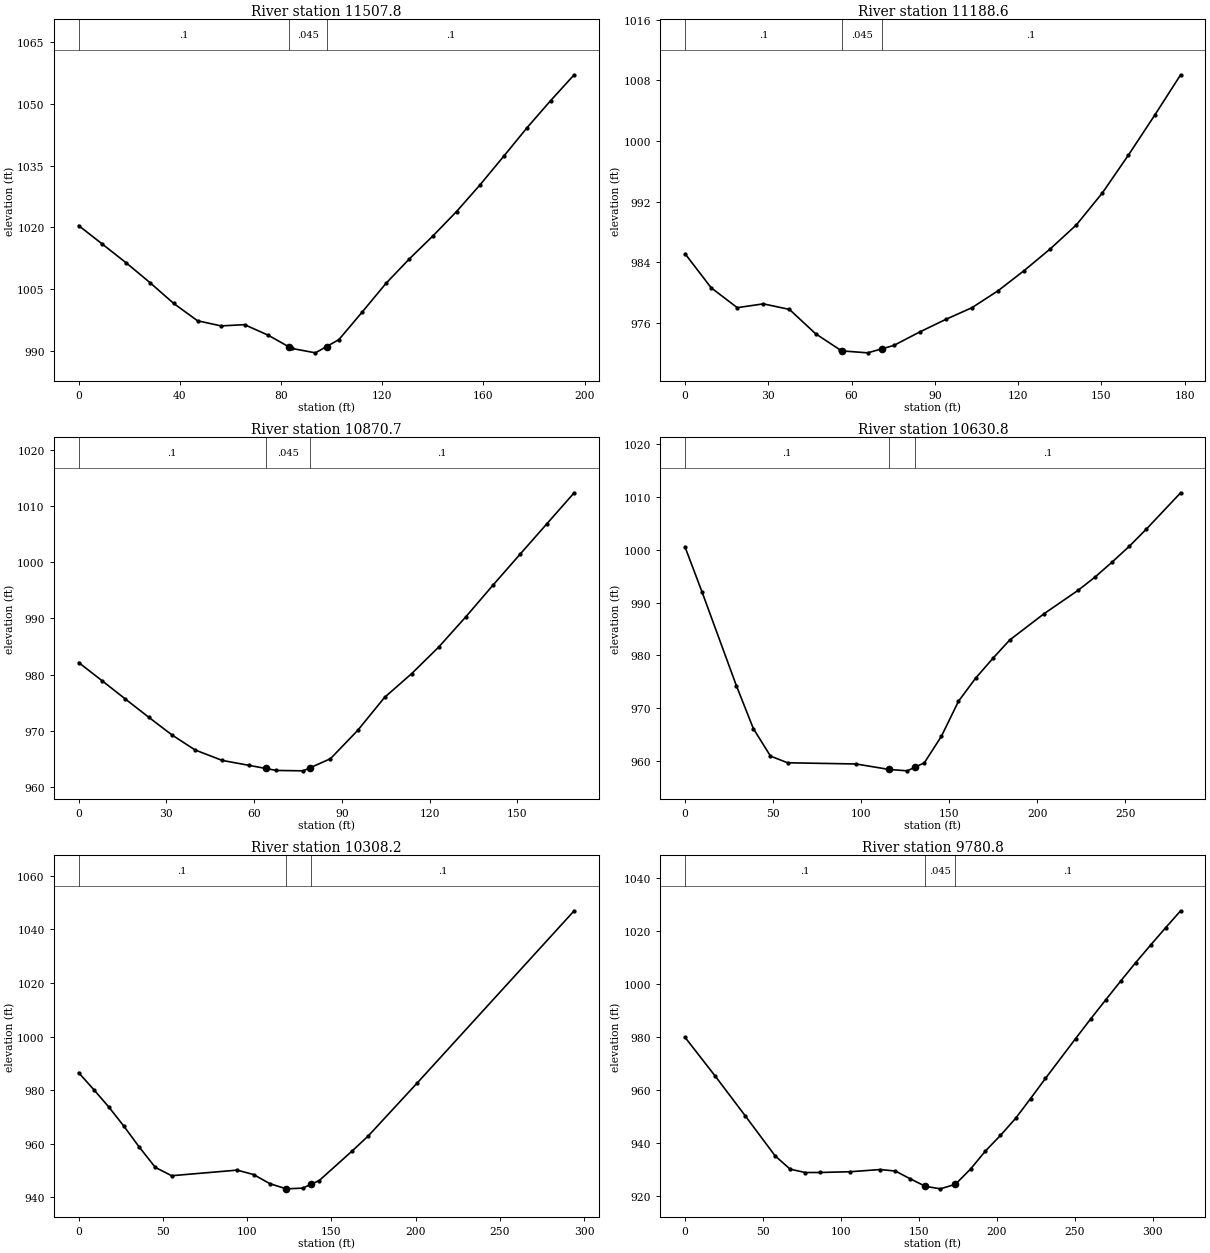
Type RM Length L Ch R = 1 ,11507.8 ,319.3,319.3,319.3
XS GIS Cut Line= 3
     1850152.894      405929.021     1850184.144      405975.896
     1850267.478      406087.876
#Sta/Elev= 24
       0 1020.45     9.4 1015.93    18.8 1011.38    28.2 1006.58    37.6  1001.5
      47   997.3    56.3  996.05    65.6  996.35      75  993.77      83     991
    84.2  990.58    93.6   989.5      98  991.02   102.9  992.72   112.2  999.49
   121.5 1006.39   130.8 1012.38   140.1 1017.95   149.4 1023.86   158.7 1030.36
     168 1037.26   177.3 1044.26   186.6 1050.83   195.9 1057.11
#Mann= 3 , 0 , 0
       0      .1       0      83    .045       0      98      .1       0
Bank Sta=83,98
XS Rating Curve= 0 ,0
Exp/Cntr=0.3,0.1

Type RM Length L Ch R = 1 ,11188.6 ,315.1,317.8,320.2
XS GIS Cut Line= 2
     1849939.353      406176.417     1850046.123      406319.646
#Sta/Elev= 22
       0  985.12     9.4  980.63    18.8  978.01    28.2  978.51    37.6  977.78
      47  974.58    55.9  972.43    56.4  972.31    65.8  972.05    70.9  972.58
    75.2  973.02    84.6  974.81      94  976.47   103.4  978.01   112.8  980.24
   122.2   982.9   131.6  985.76     141  988.92   150.4  993.15   159.8  998.15
   169.2 1003.37   178.6 1008.73
#Mann= 3 , 0 , 0
       0      .1       0    56.4    .045       0    70.9      .1       0
Bank Sta=56.4,70.9
XS Rating Curve= 0 ,0
Exp/Cntr=0.3,0.1

Type RM Length L Ch R = 1 ,10870.7 ,237.2,239.9,242.7
XS GIS Cut Line= 3
     1849725.811      406382.146     1849733.623      406421.209
     1849798.728      406533.188
#Sta/Elev= 22
       0  982.18       8  978.95    15.9  975.72    23.9  972.48    31.9  969.31
    39.8  966.64    49.1  964.78    58.3   963.9      64  963.35    67.6     963
    76.8  962.93      79  963.44    86.1  965.09    95.4  970.12   104.6  975.99
   113.8  980.18   123.1  984.93   132.4  990.32   141.6   995.9   150.9 1001.42
   160.1 1006.85   169.4 1012.34
#Mann= 3 , 0 , 0
       0      .1       0      64    .045       0      79      .1       0
Bank Sta=64,79
XS Rating Curve= 0 ,0
Exp/Cntr=0.3,0.1

Type RM Length L Ch R = 1 ,10630.8 ,320.2,322.6,324.9
XS GIS Cut Line= 2
      1849494.04      406454.195     1849605.151      406712.876
#Sta/Elev= 23
       0 1000.53     9.7  991.97    29.1   974.3    38.8  966.12    48.5  960.93
    58.2  959.66    97.1  959.43   115.8   958.4   126.2  958.13   130.8  958.85
   135.9  959.65   145.6  964.68   155.3  971.32     165  975.68   174.8  979.44
   184.4  982.93   203.9  987.91   223.3  992.36     233   994.9   242.7  997.74
   252.4 1000.72   262.1 1003.98   281.5 1010.84
#Mann= 3 , 0 , 0
       0      .1       0   115.8    .045       0   130.8      .1       0
Bank Sta=115.8,130.8
XS Rating Curve= 0 ,0
Exp/Cntr=0.3,0.1

Type RM Length L Ch R = 1 ,10308.2 ,521.5,527.5,533.3
XS GIS Cut Line= 4
     1849219.734      406579.195     1849228.415      406613.917
     1849277.026      406771.903     1849299.596      406862.181
#Sta/Elev= 19
       0  986.53       9   980.2    17.9  973.72    26.8   966.6    35.8   958.9
    45.5  951.16    55.2  948.05    94.1  950.14   103.8  948.49   113.6  945.05
     123  943.21   123.3  943.15     133  943.42     138  944.86   142.8  946.25
   162.2  957.21   171.9  962.91   201.1  982.79   294.1 1046.99
#Mann= 3 , 0 , 0
       0      .1       0     123    .045       0     138      .1       0
Bank Sta=123,138
XS Rating Curve= 0 ,0
Exp/Cntr=0.3,0.1

Type RM Length L Ch R = 1 ,9780.8  ,251,239.8,228.5
XS GIS Cut Line= 2
     1848733.623      406613.917     1848745.776      406931.626
#Sta/Elev= 29
       0   979.8    19.3  965.25    38.5  950.34    57.8  935.16    67.4  930.19
    77.1  928.92    86.7  928.94     106  929.23   125.2  930.05   134.9  929.48
   144.5  926.53   154.2  923.72   163.8  922.78   173.1  924.44   173.4  924.49
   183.1  930.22   192.7  937.05   202.3  942.89     212  949.31   221.6  956.76
   231.2  964.38   250.5  979.34   260.1  986.69   269.8  993.91   279.4 1000.99
     289 1007.92   298.7 1014.61   308.3 1021.12   317.9 1027.48
#Mann= 3 , 0 , 0
       0      .1       0   154.2    .045       0   173.1      .1       0
Bank Sta=154.2,173.1
XS Rating Curve= 0 ,0
Exp/Cntr=0.3,0.1

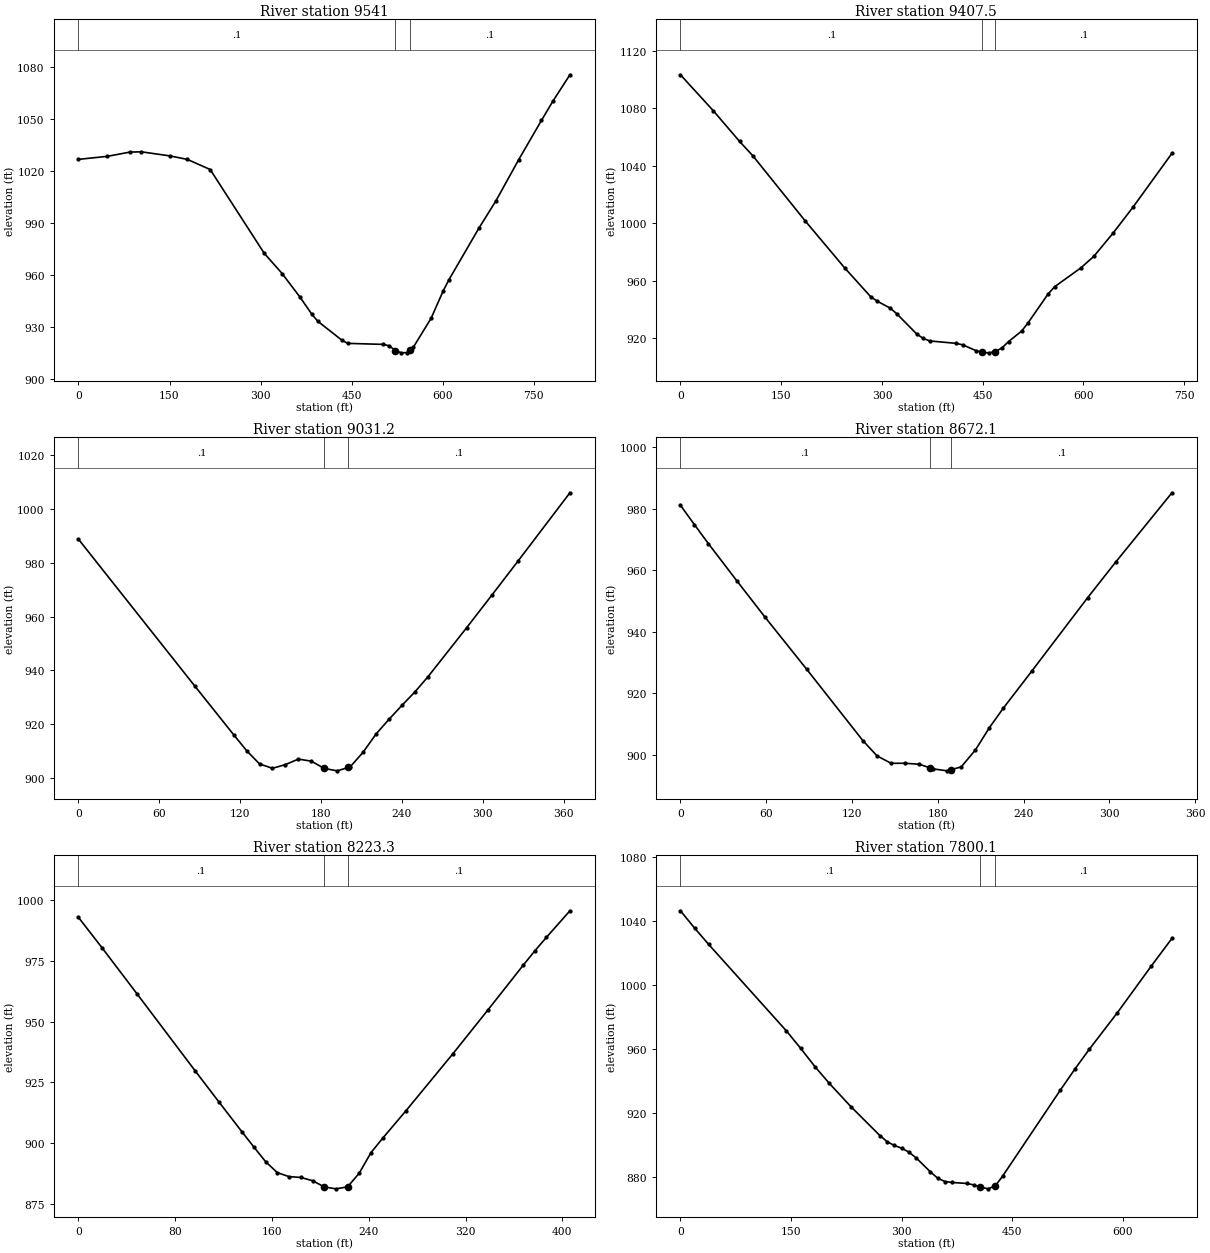
Type RM Length L Ch R = 1 ,9541    ,142.2,133.5,124.6
XS GIS Cut Line= 5
     1848228.415      406414.264     1848402.026      406544.473
     1848393.346      406633.014     1848573.901      406936.834
     1848693.693      407027.112
#Sta/Elev= 30
       0 1026.78    47.2 1028.49    84.9 1030.97   103.8 1031.12     151 1028.75
   179.3 1026.76     217 1020.91     306  972.58   335.4  960.94   364.9   947.3
   384.5  937.38   394.3  933.37   433.6  922.54   443.4  920.64   502.3  920.05
   512.1   919.2     522  916.48   531.8  915.18   541.6  915.35   546.5  916.86
   551.4  918.37   580.9  935.18   600.5  950.76   610.3  957.44   659.4  987.03
   687.5 1002.83     725 1026.58   762.5 1049.22   781.3 1060.31   809.4 1075.56
#Mann= 3 , 0 , 0
       0      .1       0     522    .045       0   546.5      .1       0
Bank Sta=522,546.5
XS Rating Curve= 0 ,0
Exp/Cntr=0.3,0.1

Type RM Length L Ch R = 1 ,9407.5  ,390.2,376.3,361.9
XS GIS Cut Line= 4
     1847995.776      406745.862     1848237.096      406784.056
     1848535.707      407004.542      1848650.29      407023.639
#Sta/Elev= 30
       0 1103.21    48.9 1078.24      88 1056.92   107.5 1047.07   185.7 1001.69
   244.3  969.12   283.4  948.91   293.2  945.86   312.7  940.96   322.5  936.94
   351.8  923.08   361.5  919.98   371.3  918.27   410.4   916.6   420.2  915.57
   439.7  911.59   449.5  910.26   459.2  910.01   468.8  910.88   478.8   913.5
   488.5  917.84   508.1  925.21   517.8  931.05   547.1  950.76   556.9  955.89
     596     969   615.5  977.09   644.6  993.53   673.6 1011.15   731.7 1048.62
#Mann= 3 , 0 , 0
       0      .1       0   449.5    .045       0   468.8      .1       0
Bank Sta=449.5,468.8
XS Rating Curve= 0 ,0
Exp/Cntr=0.3,0.1

Type RM Length L Ch R = 1 ,9031.2  ,359.5,359.1,358.6
XS GIS Cut Line= 2
     1848193.693       407282.32     1848558.276      407292.737
#Sta/Elev= 23
       0  988.71    86.4  934.18   115.2  916.15   124.8  910.24   134.4  905.31
     144  903.69   153.6  905.07   163.2   907.1   172.8  906.34   182.4  903.64
     192  902.75   200.3     904   201.6   904.2   211.2  909.63   220.8  916.39
   230.4  921.84     240  927.01   249.6     932   259.2  937.56     288  955.82
   307.1  968.16   326.3  980.67   364.7 1005.93
#Mann= 3 , 0 , 0
       0      .1       0   182.4    .045       0   200.3      .1       0
Bank Sta=182.4,200.3
XS Rating Curve= 0 ,0
Exp/Cntr=0.3,0.1

Type RM Length L Ch R = 1 ,8672.1  ,449.1,448.8,448.1
XS GIS Cut Line= 2
     1848186.748      407643.431     1848530.498      407646.903
#Sta/Elev= 23
       0  981.07     9.8  974.77    19.6  968.58    39.3  956.62    58.9  944.88
    88.4  927.74   127.7  904.56   137.5  899.66   147.3  897.24   157.2  897.25
     167  896.94   174.5  895.78   176.8  895.42   186.6  894.79   189.5  895.17
   196.4  896.08   206.3  901.55   216.1  908.81   225.9  915.19   245.6  927.09
   284.8  951.03   304.5  962.64   343.8  985.13
#Mann= 3 , 0 , 0
       0      .1       0   174.5    .045       0   189.5      .1       0
Bank Sta=174.5,189.5
XS Rating Curve= 0 ,0
Exp/Cntr=0.3,0.1

Type RM Length L Ch R = 1 ,8223.3  ,429.8,423.2,416.5
XS GIS Cut Line= 2
     1848191.957       408094.82     1848598.207      408089.612
#Sta/Elev= 25
       0  993.03    19.4  980.56    48.4  961.54    96.7  929.66   116.1  917.01
   135.4  904.53   145.1  898.38   154.8  892.35   164.4  887.87   174.1  886.22
   183.8  885.88   193.5  884.56   203.1     882   212.8  881.19   222.5     882
   232.2  887.69   241.8  896.08   251.5  902.03   270.9  913.44   309.6  936.86
   338.6  954.94   367.6  973.26   377.3  979.23   386.9   984.8   406.3  995.73
#Mann= 3 , 0 , 0
       0      .1       0   203.1    .045       0   222.5      .1       0
Bank Sta=203.1,222.5
XS Rating Curve= 0 ,0
Exp/Cntr=0.3,0.1

Type RM Length L Ch R = 1 ,7800.1  ,419.7,411.4,403.2
XS GIS Cut Line= 4
     1848110.359      408584.403     1848263.137      408573.987
     1848664.179      408445.514     1848749.248      408409.056
#Sta/Elev= 30
       0 1046.31    19.1 1035.54    38.3 1025.27   143.6  971.26   162.9  960.39
   182.5  948.84   202.1   938.3   231.5  923.71   270.6  905.74   280.4  901.93
   290.2  899.54     300  897.86   309.8   895.4   319.6  891.85   339.2  882.99
     349  879.07   358.8     877   368.6   876.4   388.2  875.79     398  874.89
   406.4  873.61   417.6  872.42   427.4  874.42   437.1  880.38   515.5  934.23
   535.1   947.3   554.7  959.72   592.8  982.59     639 1011.89   666.8 1029.03
#Mann= 3 , 0 , 0
       0      .1       0   406.4    .045       0   427.4      .1       0
Bank Sta=406.4,427.4
XS Rating Curve= 0 ,0
Exp/Cntr=0.3,0.1

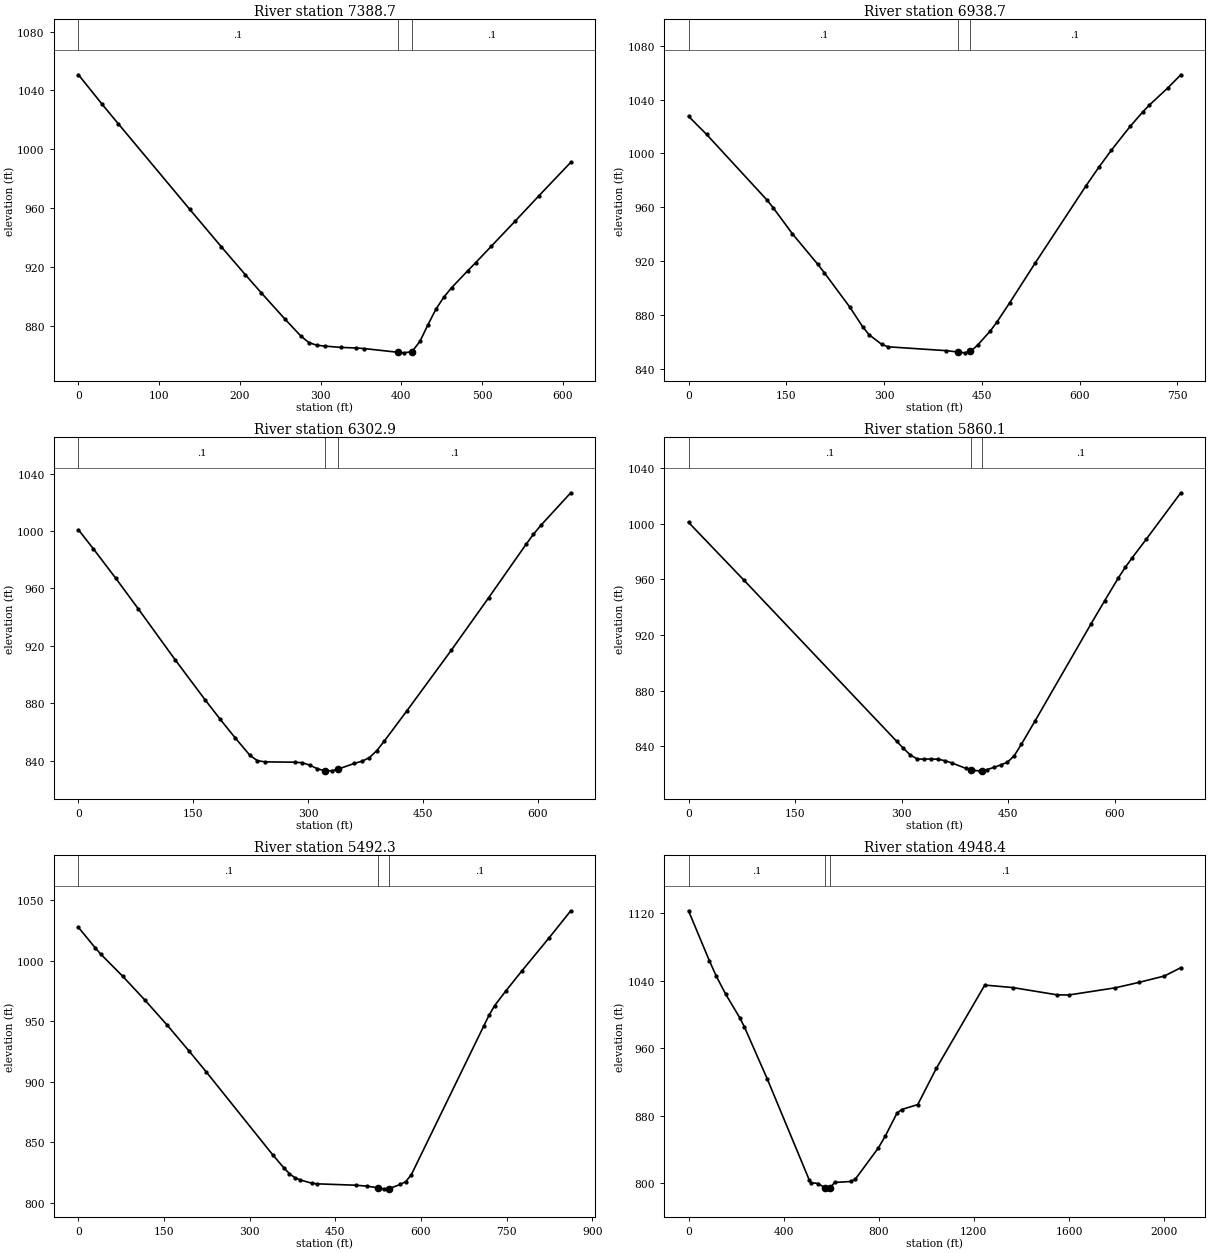
Type RM Length L Ch R = 1 ,7388.7  ,443.6,450,456.4
XS GIS Cut Line= 2
     1848441.957      409067.042     1848917.651      408685.098
#Sta/Elev= 29
       0 1050.67    29.5  1030.5    49.2 1017.45   137.8   959.2   177.1  933.61
   206.6  914.78   226.3  902.48   255.8  884.53   275.5  872.98   285.4  868.52
   295.2   866.7     305  866.12   324.7  865.22   344.4  864.82   354.2  864.42
   395.6  861.92   403.4  861.52   413.3   862.4   423.1   869.3   432.9  880.46
   442.8  891.11   452.6  899.31   462.5  905.93   482.1  917.21     492  922.76
   511.7  934.11   541.2  951.19   570.7  968.44     610  991.11
#Mann= 3 , 0 , 0
       0      .1       0   395.6    .045       0   413.3      .1       0
Bank Sta=395.6,413.3
XS Rating Curve= 0 ,0
Exp/Cntr=0.3,0.1

Type RM Length L Ch R = 1 ,6938.7  ,635.2,635.8,636.2
XS GIS Cut Line= 4
     1848652.026      409311.834     1848752.721      409266.695
     1849214.526      409075.723     1849344.734      409011.487
#Sta/Elev= 30
       0 1027.58    27.6 1014.18   120.2  965.51     130  959.63   159.3  940.38
   198.5  917.59   208.3  911.47   247.5  885.88   267.1  871.37   276.9  865.46
   296.5  858.19   306.3  856.43   394.5   853.6   414.1  852.56   423.9  851.95
   431.3  853.02   433.7  853.37   443.5  857.67   463.1  868.22   472.9  874.64
   492.5  888.91   531.7  918.49   610.1  976.14   629.4  989.64   648.8 1002.43
   677.8  1020.2   697.2 1030.93   706.9 1035.82   735.9 1048.87   755.3 1058.39
#Mann= 3 , 0 , 0
       0      .1       0   414.1    .045       0   431.3      .1       0
Bank Sta=414.1,431.3
XS Rating Curve= 0 ,0
Exp/Cntr=0.3,0.1

Type RM Length L Ch R = 1 ,6302.9  ,442.7,442.8,442.9
XS GIS Cut Line= 2
     1848804.804      409886.487     1849407.234      409660.792
#Sta/Elev= 30
       0 1000.89    19.5  987.62    48.7  967.12      78  945.89   126.7  910.01
   165.7  882.18   185.2  868.78   204.7  855.86   224.2  843.53   233.9  839.89
   243.7  839.08   282.7  838.83   292.4  838.45   302.2  836.83   311.9  834.34
   321.7  832.81   331.4  832.87   339.6  834.05   360.6  838.01   370.4   839.5
   380.1  841.98   389.9  846.93   399.6  853.54   428.9  874.47   487.4  917.08
   536.1  953.58   584.8   990.7   594.6   997.8   604.3 1004.04   643.3 1026.71
#Mann= 3 , 0 , 0
       0      .1       0   321.7    .045       0   339.6      .1       0
Bank Sta=321.7,339.6
XS Rating Curve= 0 ,0
Exp/Cntr=0.3,0.1

Type RM Length L Ch R = 1 ,5860.1  ,371.1,367.8,364.4
XS GIS Cut Line= 2
     1848912.443       410313.57     1849558.276       410063.57
#Sta/Elev= 30
       0 1001.17      78  959.47   292.6  843.55   302.4  838.34   312.1  833.53
   321.9  830.69   331.6  830.58   341.4   830.7   351.1  830.49   360.9  829.45
   370.6  827.81   390.2  823.93   397.3  822.88   399.9  822.49   409.7  822.16
   412.3  822.38   419.4  822.97   429.2  824.58   438.9  826.37   448.7  828.38
   458.4   833.2   468.2  841.27   487.7  858.29   565.7  927.58   585.2  944.52
   604.8  961.27   614.5  968.84   624.2  975.68   643.8  988.94   692.5 1022.46
#Mann= 3 , 0 , 0
       0      .1       0   397.3    .045       0   412.3      .1       0
Bank Sta=397.3,412.3
XS Rating Curve= 0 ,0
Exp/Cntr=0.3,0.1

Type RM Length L Ch R = 1 ,5492.3  ,552.4,543.9,535.3
XS GIS Cut Line= 4
     1848974.943      410748.466     1849066.089      410714.612
      1849623.38      410396.903      1849717.13      410316.174
#Sta/Elev= 30
       0 1027.62    29.2 1010.84    38.9 1005.59    77.8  987.08   116.7  967.33
   155.6   946.7   194.4     925   223.6  908.24   340.2  839.56   359.7  828.75
   369.4  824.02   379.1  820.53   388.8  818.68   408.3  816.04     418  815.48
     486  814.33   505.4  813.58   525.5  812.13   534.6  811.34   544.3   811.5
   563.8  814.99   573.5  817.39   583.2  823.13   709.6   945.7   719.3  954.99
     729  962.91   748.2  974.78   776.8  991.69   824.4 1018.96   862.4  1041.4
#Mann= 3 , 0 , 0
       0      .1       0   525.5    .045       0   544.3      .1       0
Bank Sta=525.5,544.3
XS Rating Curve= 0 ,0
Exp/Cntr=0.3,0.1

Type RM Length L Ch R = 1 ,4948.4  ,409.3,411.3,412.4
XS GIS Cut Line= 5
      1849404.63      411329.195      1849592.13       411157.32
     1850034.202      410602.112     1849987.964      410323.987
     1850618.172      409792.737
#Sta/Elev= 30
       0 1122.82      88 1063.48   117.4 1045.01   156.5 1023.94   215.2  996.26
   234.8  985.39   332.1  923.03   507.1  804.44   516.8  800.72     546  799.79
   575.6  794.15   584.9  793.48   594.6  794.37   614.1  801.01   682.1  802.18
   701.6  804.96   798.8  842.13     828  856.27   876.6  883.04     896   887.4
   964.1  893.28  1041.8  936.03    1246 1034.81  1363.8 1031.88  1550.2 1023.26
  1599.3 1023.08  1795.5 1031.61  1893.6 1037.95  2001.6 1045.58  2070.3 1055.42
#Mann= 3 , 0 , 0
       0      .1       0   575.6    .045       0   594.6      .1       0
Bank Sta=575.6,594.6
XS Rating Curve= 0 ,0
Exp/Cntr=0.3,0.1

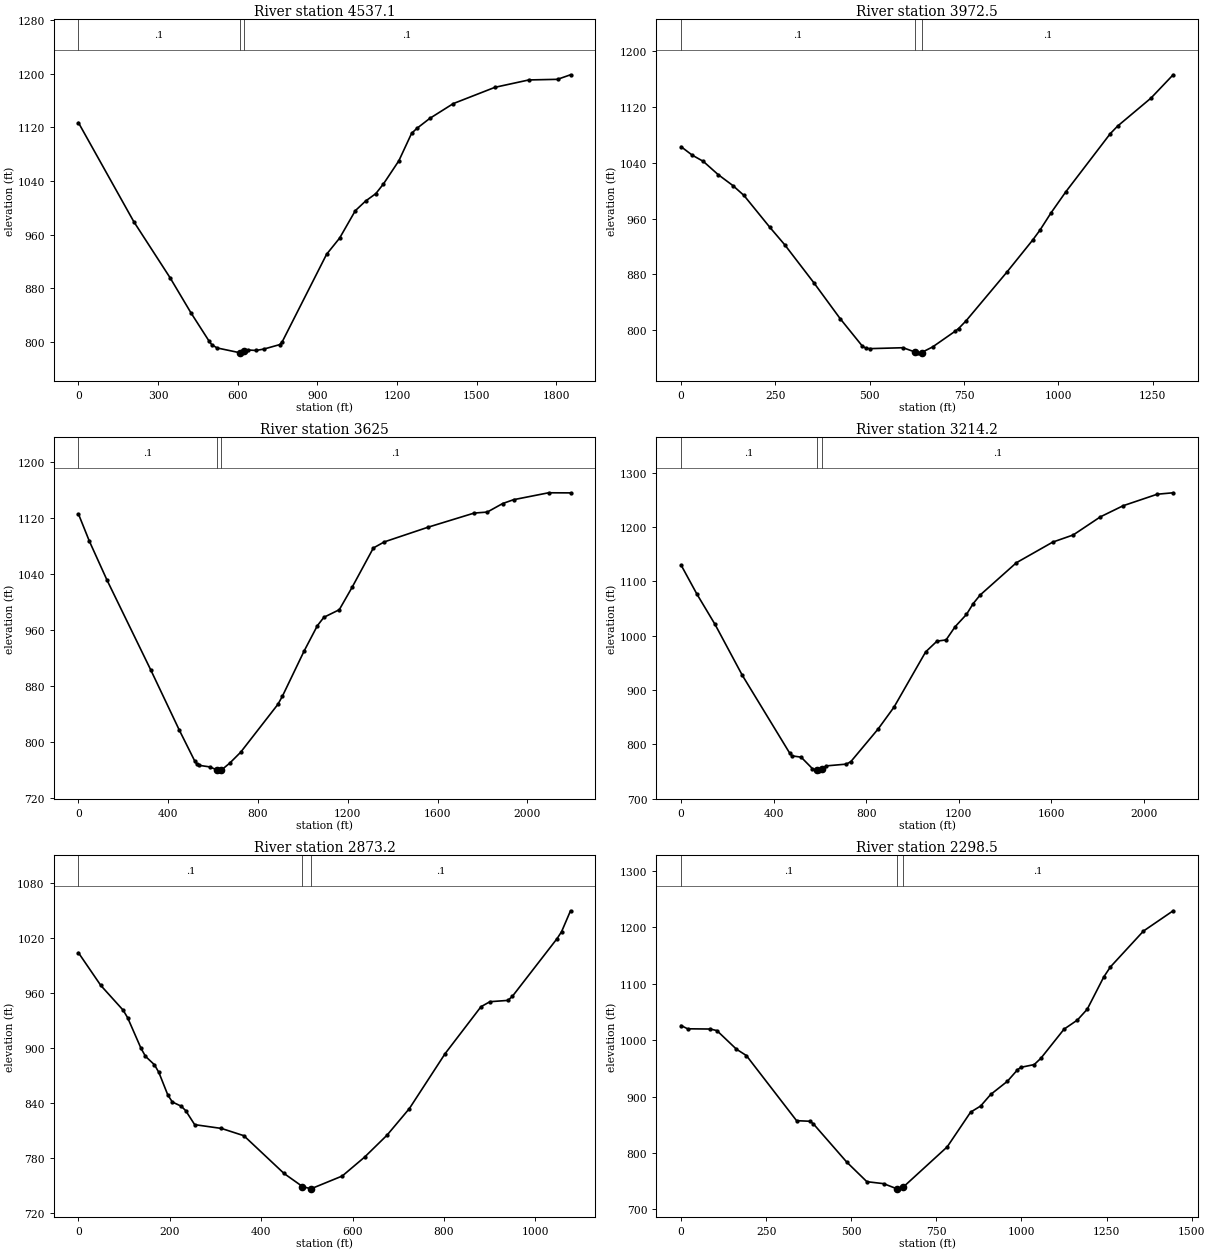
Type RM Length L Ch R = 1 ,4537.1  ,563.7,564.6,565.3
XS GIS Cut Line= 5
     1849680.672      411587.008      1849842.13      411441.174
     1850407.234      410826.591     1850605.151      410784.924
     1851024.422      410357.841
#Sta/Elev= 30
       0 1126.79   208.1  979.49   345.3  895.58   423.8  843.37   492.6   800.9
   502.4  795.87   522.1  791.12   608.1  783.94   610.5  783.82   623.1  785.94
   639.9  788.04   669.4  787.36   698.9   789.5   757.8  796.06   767.6  800.43
   934.6  930.72   983.7  954.86  1042.6  995.58  1081.4    1010  1119.9 1021.05
  1148.8 1035.57  1206.6 1069.94  1254.7 1110.89  1274.3 1118.21  1323.4 1133.23
  1411.7 1155.22  1568.7 1179.49  1696.2 1190.46  1804.2 1191.38  1853.2 1198.16
#Mann= 3 , 0 , 0
       0      .1       0   608.1    .045       0   623.1      .1       0
Bank Sta=608.1,623.1
XS Rating Curve= 0 ,0
Exp/Cntr=0.3,0.1

Type RM Length L Ch R = 1 ,3972.5  ,346,347.6,349
XS GIS Cut Line= 2
     1850107.755       411919.82     1851019.214      410987.528
#Sta/Elev= 30
       0 1062.95    29.4 1050.89    58.8 1041.94      98 1023.06   137.2 1007.26
   166.6  993.11   235.3  947.33   274.5  922.48   352.9  867.17   421.5   816.5
   480.4  777.07   490.2  774.05     500  773.52   588.2  774.83     620  768.66
   627.4   767.5   637.2  767.97   666.6     776   725.4  798.18   735.2  802.31
   754.8  813.19   862.7  882.83   931.3  928.94   950.9  943.36   980.3  968.18
  1019.5  998.37  1137.2 1081.65  1156.8 1092.57    1245 1132.59  1303.8 1166.04
#Mann= 3 , 0 , 0
       0      .1       0     620    .045       0   637.2      .1       0
Bank Sta=620,637.2
XS Rating Curve= 0 ,0
Exp/Cntr=0.3,0.1

Type RM Length L Ch R = 1 ,3625    ,401.4,410.8,420.1
XS GIS Cut Line= 4
      1850310.88      412148.987     1851175.464      411372.945
     1851191.089      411221.903     1851972.339      410820.862
#Sta/Elev= 30
       0 1125.91    48.8 1086.86   126.9 1031.48   322.2  902.62   449.1  816.65
   517.4  772.69   527.2  768.18     537  766.19   585.8  763.85     617  759.52
   624.8  758.27   634.6  758.87   673.6  769.23   722.4  784.85   888.4  853.48
     908   864.8  1005.6  930.05  1064.2  966.04  1093.4  978.11  1161.8  988.89
  1218.7 1020.87  1313.6 1077.27  1362.4    1086  1557.6 1107.06  1762.5 1127.25
    1821 1128.68  1889.3 1140.86  1938.1  1146.4  2094.2  1156.3  2191.8 1156.15
#Mann= 3 , 0 , 0
       0      .1       0     617    .045       0   634.6      .1       0
Bank Sta=617,634.6
XS Rating Curve= 0 ,0
Exp/Cntr=0.3,0.1

Type RM Length L Ch R = 1 ,3214.2  ,344.5,341,337.2
XS GIS Cut Line= 4
     1850378.589      412289.612     1851420.255      411945.862
     1851555.672      412003.153     1852378.589      411680.237
#Sta/Elev= 30
       0 1129.75    68.6 1076.16   146.9 1020.47   264.4  927.11   470.1   783.3
   479.9  778.54   519.1  776.17     568  755.06   587.6  751.71   597.4  750.99
   608.2  753.69   626.8  760.05     715  763.38   734.5  768.11   852.1  828.02
   920.6   868.1  1057.7  969.94  1106.7  989.71  1145.9  991.96  1185.1 1016.28
  1234.2 1038.88  1263.6 1058.96  1293.1 1074.49  1450.2 1134.08  1607.4 1172.04
  1695.8 1185.16  1813.6 1218.57  1911.9 1238.98  2059.2 1260.15    2128  1262.8
#Mann= 3 , 0 , 0
       0      .1       0   587.6    .045       0   608.2      .1       0
Bank Sta=587.6,608.2
XS Rating Curve= 0 ,0
Exp/Cntr=0.3,0.1

Type RM Length L Ch R = 1 ,2873.2  ,562.8,574.7,587.2
XS GIS Cut Line= 3
     1850670.921      412644.212     1851080.643      412415.046
     1851618.838      412133.796
#Sta/Elev= 30
       0 1003.78    48.9  968.16    97.8  941.21   107.6  933.01   136.9  899.64
   146.7  890.92   166.3  881.75     176  873.35   195.6  848.77   205.4  841.22
     225  836.59   234.7  831.75   254.3  816.52     313  812.39   361.9  804.49
   449.9  763.32   490.1  749.14   508.6   746.6   577.2  760.57   626.2   781.2
   675.1  805.01   724.1  834.05   802.5  894.02   880.8  944.99   900.4  950.45
   939.6  951.88   949.4  956.25  1047.3 1019.19  1057.1 1026.68  1076.7  1049.5
#Mann= 3 , 0 , 0
       0      .1       0   490.1    .045       0   508.6      .1       0
Bank Sta=490.1,508.6
XS Rating Curve= 0 ,0
Exp/Cntr=0.3,0.1

Type RM Length L Ch R = 1 ,2298.5  ,2021.7,2006.8,1990.9
XS GIS Cut Line= 4
     1850607.755      412961.487      1850779.63      412971.903
     1851675.464      412846.903     1852024.422      412727.112
#Sta/Elev= 30
       0 1025.91    19.1  1020.1    86.1 1019.67   105.2 1016.91   162.6  983.94
   191.8  972.67   339.3  857.16   378.7  856.14   388.5  851.65   486.8  783.66
   545.8  748.99     595  745.49   634.3   736.3   652.9  739.56   781.8   810.7
   850.6   872.3   880.1  883.19   909.6  903.66   958.7  927.07   988.2  947.31
     998  951.73  1037.4  956.63    1057  967.82  1125.2 1019.51  1164.1  1035.5
  1193.2  1054.8  1241.8    1112  1261.2 1129.74  1358.3 1193.37  1445.6 1229.37
#Mann= 3 , 0 , 0
       0      .1       0   634.3    .045       0   652.9      .1       0
Bank Sta=634.3,652.9
XS Rating Curve= 0 ,0
Exp/Cntr=0.3,0.1

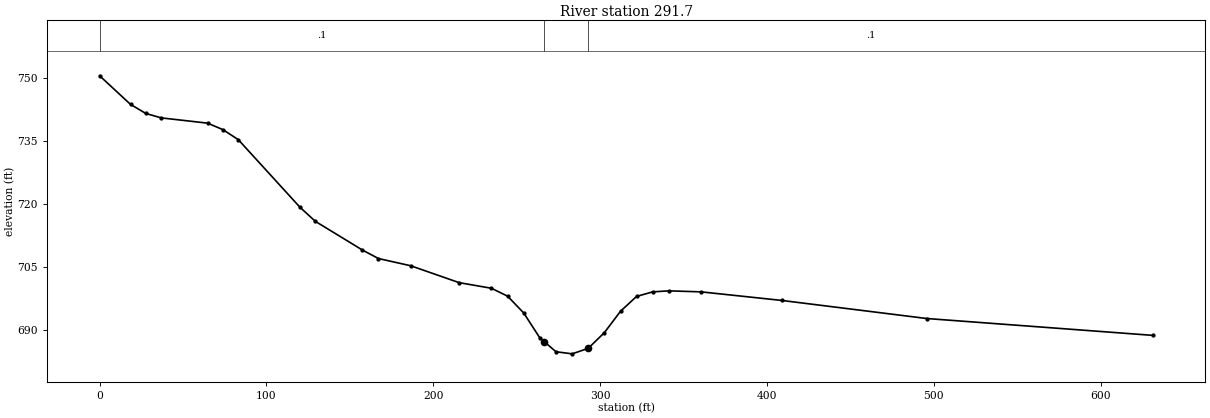
Type RM Length L Ch R = 1 ,291.7   ,281.5,291.7,302.2
XS GIS Cut Line= 3
     1852630.542      414271.166     1852750.472      414184.775
     1853142.695      413902.242
#Sta/Elev= 30
       0   750.5    18.5  743.69    27.7  741.52      37  740.47    64.7  739.22
    73.9  737.67    83.1  735.29   120.1  719.18   129.3  715.83   157.5     709
   167.1  706.98   186.5  705.25   215.5  701.23   234.8   699.9   244.5  698.02
   254.2     694   263.8   688.1   266.4  687.21   273.5  684.78   283.2  684.28
   292.8  685.58   302.5  689.32   312.2  694.42   321.8  697.95   331.5  699.04
   341.2  699.28   360.5  699.04   408.8     697   495.8  692.69   631.2  688.68
#Mann= 3 , 0 , 0
       0      .1       0   266.4    .045       0   292.8      .1       0
Bank Sta=266.4,292.8
XS Rating Curve= 0 ,0
Exp/Cntr=0.3,0.1

Chan Stop Cuts=-1
Use User Specified Reach Order=0
Composite Channel Slope=5